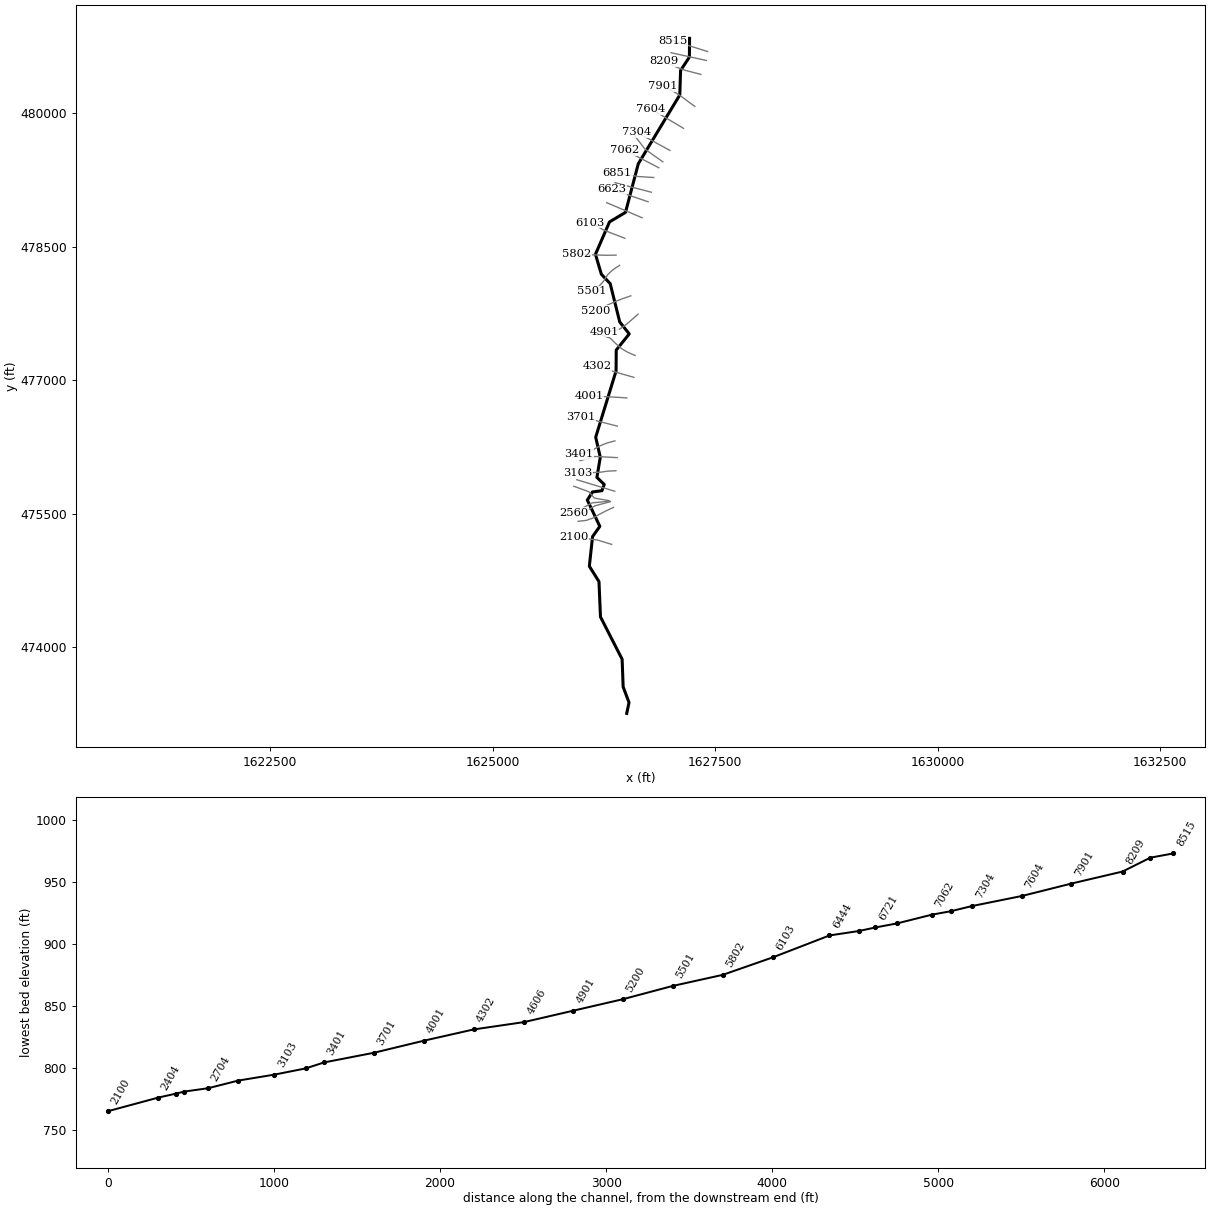
--- WstFkLwrBwmRn.prj (project) ---

Proj Title=WstFkLwrBwmRn
Current Plan=p01
Default Exp/Contr=0,0
English Units
Geom File=g01
Flow File=f01
Plan File=p01
BEGIN DESCRIPTION:
---------- MODELED AS PART OF WVEM CTP PROGRAM, 2025----------
Stream Name: West Fork Lower Bowman Run
Flood Zone: AFH
Marshall County, WV
HEC-RAS Version: RAS 6.6
Vertical Datum: NAVD88
Projection: NAD 1983 StatePlane West Virginia N FIPS 4701 (US Feet)
Terrain: 1-meter West Virginia FEMA R3 South Central (collected 2018-2019)
Land Use: 2024 NLCD
Hydrologic Method:
Duda et al., "Estimation of magnitude and frequency of floods for rural, unregulated streams in and near Virginia and West Virginia." September 8, 2025.
Additional Model Notes:
Coincident peak modeled as normal depth
END DESCRIPTION:
DSS Export Rating Curves= 0
DSS Export Rating Curve Sorted= 0
DSS Export Volume Flow Curves= 0
DXF OffsetX= 0
DXF OffsetY= 0
DXF ScaleX= 0
DXF ScaleY= 0

--- WstFkLwrBwmRn.p01 (plan) ---

Plan Title=Floodplain
Program Version=6.60
Short Identifier=Floodplain
Geom File=g01
Flow File=f01
Subcritical Flow
K Sum by GR= 0
Std Step Tol= 0.01
Critical Tol= 0.01
Num of Std Step Trials= 20
Max Error Tol= 0.3
Flow Tol Ratio= 0.001
Split Flow NTrial= 30
Split Flow Tol= 0.02
Split Flow Ratio= 0.02
Log Output Level= 0
Friction Slope Method= 1
Unsteady Friction Slope Method= 2
Unsteady Bridges Friction Slope Method= 1
Parabolic Critical Depth
Global Vel Dist= 0 , 0 , 0
Global Log Level= 0
CheckData=False
Encroach Param=-1 ,0,0, 0
Flow Ratio Tolerance=0.1
Flow Ratio Min Ratio=0.5
Flow Ratio Max Ratio=4
Flow Ratio Max Iterations= 10
Mapping Interval=1HOUR
Computation Time Step Use Courant=        0
Computation Time Step Use Time Series=    0
Computation Time Step Count To Double=0
Computation Time Step Max Doubling=0
Computation Time Step Max Halving=0
Computation Time Step Residence Courant=0
Run HTab= 0
Run UNet= 0
Run Sediment= 0
Run PostProcess= 0
Run WQNet= 0
Run RASMapper=-1
UNET Theta= 0
UNET Theta Warmup= 0
UNET ZTol= 0
UNET ZSATol= 0
UNET MxIter= 0
UNET Max Iter WO Improvement= 0
UNET MaxInSteps= 0
UNET DtIC= 0
UNET DtMin= 0
UNET MaxCRTS= 0
UNET WFStab= 0
UNET SFStab= 0
UNET WFX= 1
UNET SFX= 1
UNET Gravity=32.17405
UNET 1D Methodology=Finite Difference
UNET DSS MLevel= 1
UNET Pardiso=0
UNET DZMax Abort= 0
UNET Use Existing IB Tables= 0
UNET Froude Reduction=False
UNET Froude Limit= 0
UNET Froude Power= 0
UNET D1 Cores= 0
UNET WindReference=Eulerian
UNET WindDragFormulation=Hsu (1988)
UNET D2 Coriolis=0
UNET D2 Cores= 0
UNET D2 Theta= 1
UNET D2 Theta Warmup= 1
UNET D2 Z Tol= 0.01
UNET D2 Volume Tol= 0.01
UNET D2 Max Iterations= 20
UNET D2 Advanced Convergence=0
UNET D2 WS Max Tol=0.15
UNET D2 WS RMS Tol=0.002
UNET D2 WS Stall Tol=1
UNET D2 Equation= 0
UNET D2 RampUpFraction=0.1
UNET D2 TimeSlices= 1
UNET D2 Turbulence Formulation=Non-Conservative (original)
UNET D2 Eddy Viscosity=0.3
UNET D2 Transverse Eddy Viscosity=0.1
UNET D2 Smagorinsky Mixing=0
UNET D2 BCVolumeCheck=0
UNET D2 Cores=0
UNET D2 SolverType=PARDISO (Direct)
UNET D2 Minimum Iterations= 3
UNET D2 Maximum Iterations= 30
UNET D2 Restart Number= 10
UNET D2 Relaxation Coeff=1.3
UNET D2 SOR Precondition Iterations= 10
UNET D2 ILUT Maximum Fill= 8
UNET D2 ILUT Tolerance=1E-08
UNET D2 Convergence Tolerance=0.00001
PS Theta= 1
PS WS Tol= 0.01
PS Volume Tol= 0.01
PS Max Iterations= 20
PS Equation= 0
PS Advance Time Step=-1
PS Target Courant=0.9
PS Time Slices= 1
PS Iterate With 2D=0
PS Project Initial WSE from DS=-1
PS Ramp Up Initial WSE from US=-1
PS Cores=0
UNET D1D2 MaxIter= 0
UNET D1D2 ZTol=0.01
UNET D1D2 QTol=0.1
UNET D1D2 MinQTol=1
Write IC File= 0
Write IC File at Fixed DateTime=0
Write IC File at Sim End=0
Echo Input=False
Echo Parameters=False
Echo Output=False
Write Detailed= 0
HDF Write Warmup=0
HDF Write Time Slices=0
HDF Flush=0
HDF Compression= 1
HDF Chunk Size= 1
HDF Spatial Parts= 1
HDF Use Max Rows=0
HDF Fixed Rows= 1
Calibration Method= 0
Calibration Iterations= 20
Calibration Max Change=0.05
Calibration Tolerance=0.2
Calibration Maximum=1.5
Calibration Minimum=0.5
Calibration Optimization Method= 1
WQ AD Non Conservative
WQ ULTIMATE=-1
WQ Max Comp Step=1HOUR
WQ Output Interval=15MIN
WQ Output Selected Increments= 0
WQ Create Restart=0
WQ Fixed Restart=0
WQ System Summary=0
WQ Write To DSS=0
Sorting and Armoring Iterations= 10
XS Update Threshold= 0.02
Bed Roughness Predictor= 0
Processes Affected by Predictor=Sediment Only
Hydraulics Update Threshold= 0.02
Energy Slope Method= 1
Volume Change Method= 1
Sediment Retention Method= 0
Sediment TS Multiplier= 1
Warm Up Method= 0
XS Weighting Method= 0
Number of US Weighted Cross Sections= 1
Number of DS Weighted Cross Sections= 1
Upstream XS Weight=0
Main XS Weight=1
Downstream XS Weight=0
Number of DS XS's Weighted with US Boundary= 1
Upstream Boundary Weight= 1
Weight of XSs Associated with US Boundary= 0
Number of US XS's Weighted with DS Boundary= 1
Downstream Boundary Weight= 0.5
Weight of XSs Associated with DS Boundary= 0.5
Percentile Method= 0
Sediment Output Level= 3
Mass or Volume Output= 0
Output Increment Type= 1
Profile and TS Output Increment= 1
Transport Output Increment 1
XS Output Flag= 0
XS Output Increment= 10
Read HDF5 Sediment Hotstart= 0
Sediment Hotstart Type= 0
Write Gradation File= 0
Read Gradation Hotstart= 0
Write HDF5 File= 1
Write Binary Output= 1
Write DSS Sediment File= 0
DSS Sediment Output Type= 1
SV Curve= 0
Specific Gage Flag= 0
Subcell Erosion Methods= 0
Subcell Deposition Methods= 0
Advection Scheme= 1
Matrix Solver= 0
Implicit Weighting Factor= 1
Maximum Outer Loop Convergence Iterations= 5
Convergence Maximum Absolute= 0.001
Convergence RMSE= 0.0001
Grain Fractions Max Abs Error= 0.001
Max Subgrid Regions= 1
Max Subgrid Length Scale= 3.402823E+38
Initial Layer Thickness= 3
Min Layer Thickness= 0.1
Max Layer Thickness= 6
Number of Layers= 5

--- WstFkLwrBwmRn.f01 (steady flow) ---

Flow Title=Flow
Program Version=6.60
Number of Profiles= 1
Profile Names=P100yr
River Rch & RM=WstFkLwrBwmRn,Main,8515
     833
River Rch & RM=WstFkLwrBwmRn,Main,4901
     951
River Rch & RM=WstFkLwrBwmRn,Main,3401
    1050
Boundary for River Rch & Prof#=WstFkLwrBwmRn,Main            , 1
Up Type= 0
Dn Type= 3
Dn Slope=0.064
DSS Import GetInterval= 0
DSS Import GetPeak= 0
DSS Import FillOption= 0

--- WstFkLwrBwmRn.g01 (geometry) ---

Geom Title=Geometry
Program Version=6.60

River Reach=WstFkLwrBwmRn   ,Main
Reach XY= 30
     1627213.245480841.113999993     1627211.258480630.082000002
     1627112.418480480.199000016     1627103.384480205.123999998
     1626637.039479431.531000003 1626493.2744676 478885.80517748
1626313.70900001478778.479000002     1626155.867478414.695999995
1626222.18000002478191.0090000181626321.64800002478084.535999998
     1626428.588477654.908000007     1626535.528477519.947999999
1626389.36100002477338.758000001     1626387.493477104.329999998
1626158.66900001476359.9529999941626210.03800002476134.864999995
     1626172.361475908.3760000171626254.50836699475828.816557541
1626229.09988733475759.0279333291626122.45000002475744.593999997
     1626064.469 475653.439000011626205.09300001475357.996999994
1626123.48100001475243.5230000021626087.13600002474910.327999994
1626195.51700002474737.311000004     1626212.384474340.623000026
1626455.51899999473865.574000001     1626467.081473554.768000007
1626533.05000001473378.6219999941626507.21400002473256.938999996

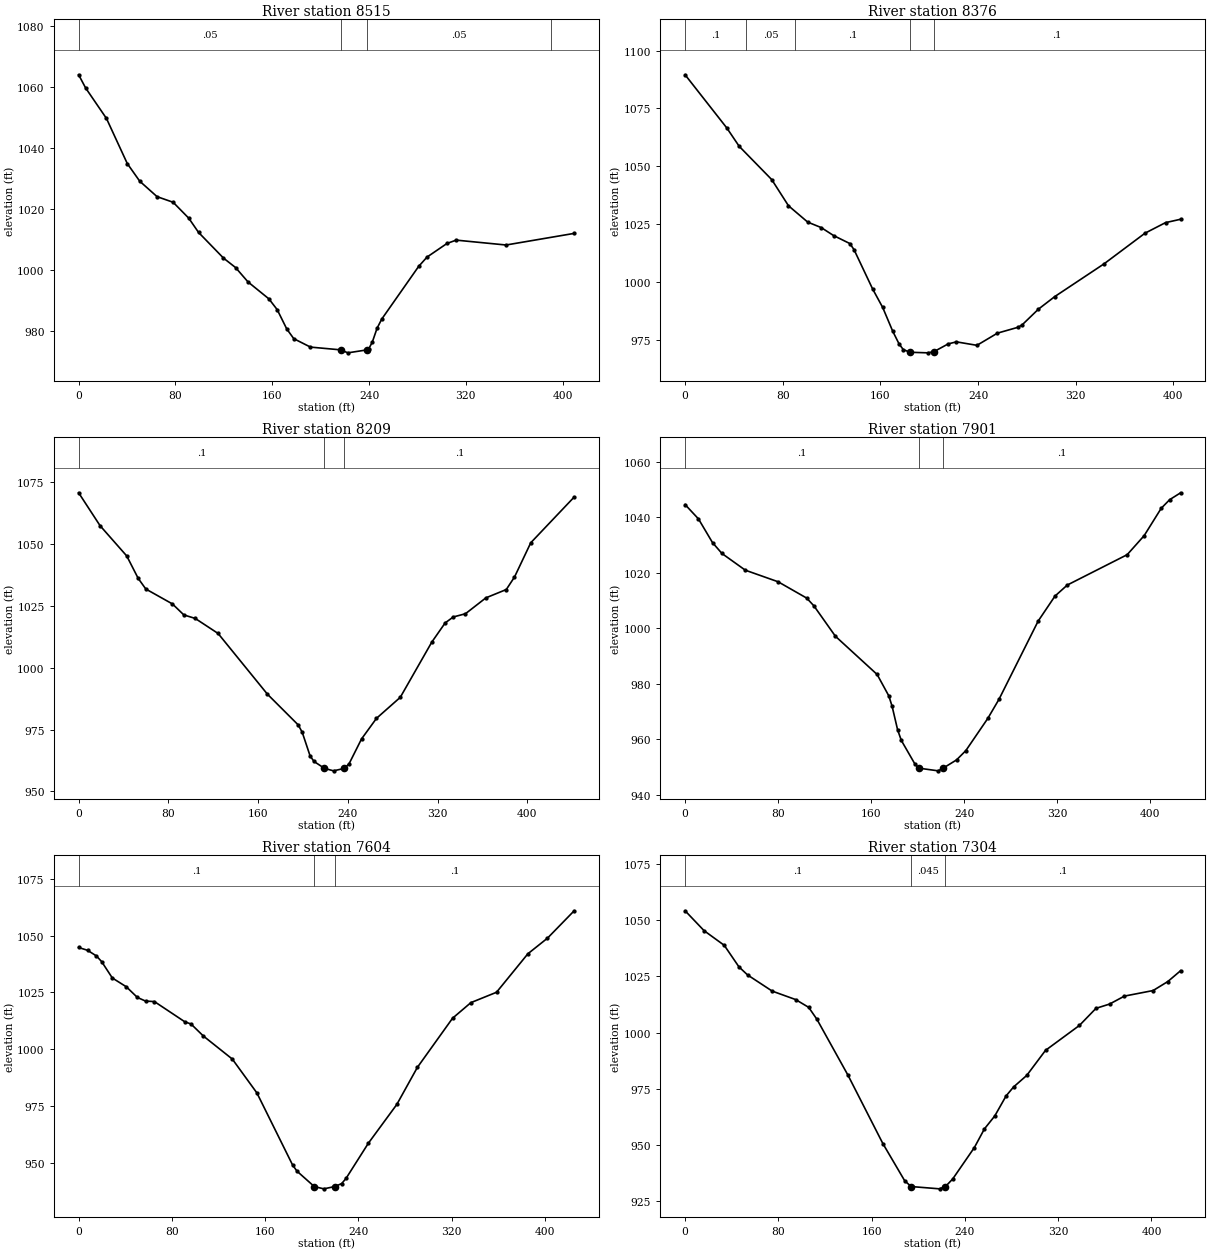
Type RM Length L Ch R = 1 ,8515    ,134.1,139.1,136.7
XS GIS Cut Line= 2
1627416.47708339480692.5418102521627025.92493489480815.638133238
#Sta/Elev= 30
       0 1064.14     5.8  1059.8      23 1049.82    40.2 1035.03    50.5 1029.24
    64.8 1024.18    78.1 1022.33      91 1017.12    99.1 1012.45   119.7 1004.03
   129.7 1000.92     140   996.2   157.2  990.67   164.1  987.12     172  980.78
   177.8   977.6   191.6  974.84   216.5  973.94   222.5  972.96  237.98973.9109
   239.7  974.26   242.7   976.5   246.6  981.01   250.5  984.04     281 1001.31
   287.9 1004.36   304.4 1008.83     312 1009.92   353.2 1008.32   409.5 1012.13
#Mann= 4 ,-1,0
       0     .05       0   216.5    .045       0  237.98     .05       0
     390      .1       0
Bank Sta=216.5,237.98
XS Rating Curve= 0 ,0
Exp/Cntr(USF)=0,0
Exp/Cntr=0.3,0.1

Type RM Length L Ch R = 1 ,8376    ,168.1,167.3,165
XS GIS Cut Line= 2
1627401.72131887480592.5290518351627005.14161978 480679.55626358
#Sta/Elev= 30
       0 1089.54    34.2 1066.57    44.3 1058.68      71 1044.29    84.7 1033.01
   100.5 1025.94   111.5  1023.6   121.6 1020.17     135 1016.69   138.4 1014.07
   153.6  997.14   161.9  989.11   170.1  978.87   175.3  973.38   178.7  970.97
   184.1969.7833   198.8  969.53   203.9970.0518   215.6   973.4   222.3  974.27
   239.1  972.77   255.9  978.03   272.7  980.55   276.1  981.58   289.5  988.39
   302.9  993.82   343.3 1007.96   376.8 1021.17   393.6 1025.72     406 1027.19
#Mann= 5 ,-1,0
       0      .1       0      50     .05       0      90      .1       0
   184.1    .045       0   203.9      .1       0
Bank Sta=184.1,203.9
XS Rating Curve= 0 ,0
Exp/Cntr(USF)=0,0
Exp/Cntr=0.3,0.1

Type RM Length L Ch R = 1 ,8209    ,310.2,308,304.3
XS GIS Cut Line= 6
1627340.84623617480435.6348989161627247.78867951480460.207028255
1627168.46370693480480.3408462551627073.26409417480514.274177343
1627005.54933459480546.5188634991626926.54883642480584.137554675
#Sta/Elev= 30
       0 1070.61    19.1 1057.33    42.9 1045.09    53.1 1036.04    59.9 1031.75
    83.6 1025.73    93.8 1021.29   103.9 1019.88   124.3 1013.81   168.3  989.28
   195.7  976.89   199.3  973.91   206.3  964.38   209.8  962.13  219.15 959.336
   227.2  958.34  236.94 959.338   241.1  961.23   252.2  971.24   265.5  979.54
   286.7  988.02   314.8 1010.32   326.7 1018.06   333.9 1020.46   344.8 1021.77
     363 1028.18   381.2 1031.55   388.5 1036.58     403 1050.42   441.7 1068.88
#Mann= 3 ,-1,0
       0      .1       0  219.15    .045       0  236.94      .1       0
Bank Sta=219.15,236.94
XS Rating Curve= 0 ,0
Exp/Cntr(USF)=0,0
Exp/Cntr=0.3,0.1

Type RM Length L Ch R = 1 ,7901    ,296.4,297.2,297.8
XS GIS Cut Line= 6
1627272.66527018480076.7435563361627201.42558326480127.542995423
1627141.71047959480172.9202012571627058.66569817480228.916808426
1626992.68059392480265.5715907511626913.64335042480304.675187096
#Sta/Elev= 30
       0 1044.56    11.5  1039.4    23.6 1030.85    31.7 1026.95    51.8 1020.93
      80 1016.76   104.6 1010.88   110.8 1008.09   129.3  997.14   165.2  983.37
   175.3  975.62   178.1  971.88   182.8  963.47     186  959.62   197.9  950.97
  201.34949.6104   217.7  948.66  221.92949.6102   233.5  952.59   241.5  955.94
   260.4  967.54     270   974.4   303.7 1002.58   318.2  1011.6   328.8 1015.58
   380.3 1026.51   394.9 1033.36   409.6 1043.23   416.9 1046.34   426.3 1048.81
#Mann= 3 ,-1,0
       0      .1       0  201.34    .045       0  221.92      .1       0
Bank Sta=201.34,221.92
XS Rating Curve= 0 ,0
Exp/Cntr(USF)=0,0
Exp/Cntr=0.3,0.1

Type RM Length L Ch R = 1 ,7604    ,299.2,300,300.4
XS GIS Cut Line= 6
 1627145.1888191479829.7105858331627070.09677768479874.627162665
1627005.73273318479913.1267575921626919.91335101479964.459988251
1626855.54897842480002.9595831781626780.45726509480047.875503838
#Sta/Elev= 30
       0 1044.76     7.7 1043.52    15.3 1041.03    19.7 1038.58    28.9 1031.36
    40.9 1027.49    50.4  1022.8    57.4 1021.21      65 1020.99    91.1 1012.09
    96.4 1011.13     107 1005.84   131.8  995.72   152.9  980.83   183.5  949.16
   187.3  946.44  202.13939.6719   210.3  938.68  219.53939.6716   225.6  940.99
   229.4  943.31   248.5  958.74   272.9  975.78   290.5  992.05   320.7 1013.67
   336.4 1020.52   358.4 1025.08   385.3    1042   402.1 1048.86     425  1060.9
#Mann= 3 ,-1,0
       0      .1       0  202.13    .045       0  219.53      .1       0
Bank Sta=202.13,219.53
XS Rating Curve= 0 ,0
Exp/Cntr(USF)=0,0
Exp/Cntr=0.3,0.1

Type RM Length L Ch R = 1 ,7304    ,128.7,129.5,128.1
XS GIS Cut Line= 6
1626992.12285225479582.1366059181626915.35299267479624.120117754
1626849.54997468479660.105938166 1626761.8132735479708.087141424
 1626696.0102555479744.0732899161626619.24006784479786.056801751
#Sta/Elev= 30
       0 1054.16    16.3 1045.31    33.6  1038.8    46.2 1029.22    53.6 1025.64
    74.7 1018.46    94.8  1014.7     106 1011.24   113.1  1005.9   139.7  981.08
   169.6  950.71   188.3   934.2  193.83931.6031   218.2  930.58   223.3 931.605
   229.5  934.96   248.1  948.94   256.7  957.21   265.6  962.98   275.3  971.88
   281.7  975.85     293  980.98   309.1  992.12   338.2 1003.21   352.4  1010.8
     364 1012.69   376.8 1016.24   401.4 1018.71     414 1022.71     425 1027.54
#Mann= 3 ,-1,0
       0      .1       0  193.83    .045       0   223.3      .1       0
Bank Sta=193.83,223.3
XS Rating Curve= 0 ,0
Exp/Cntr(USF)=0,0
Exp/Cntr=0.3,0.1

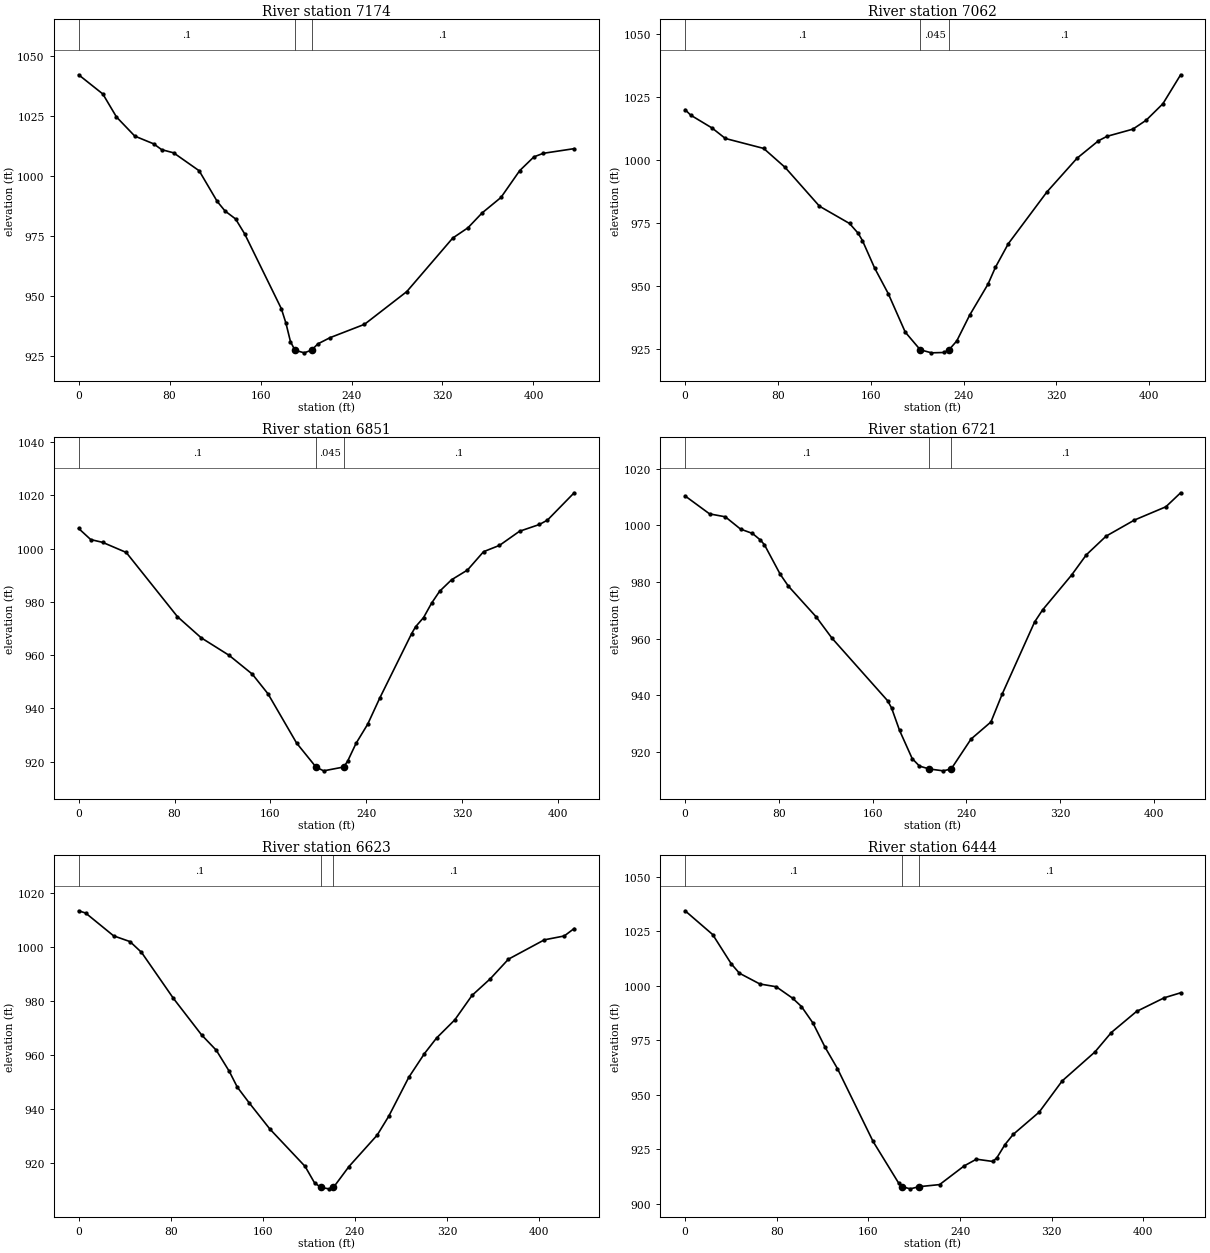
Type RM Length L Ch R = 1 ,7174    ,109.6,112.3,114.6
XS GIS Cut Line= 3
 1626913.1571618479453.464027215 1626712.6640917479596.122557862
 1626596.9950128479746.492360435
#Sta/Elev= 30
       0 1042.37    21.3 1034.35    33.3 1024.75    49.4 1016.78      66 1013.55
      73 1011.13    83.5 1009.81     106 1002.32   121.9   989.5   128.8  985.52
     138  982.23     146  976.01   178.3  944.75   182.3  938.75   186.3  931.03
  190.23 927.455   198.4  926.35   204.8  927.47   210.5  930.12   221.2   932.7
   251.4  938.25   288.6  951.91     329  974.24   342.4  978.53   354.8  984.71
   371.4  991.17   387.9 1002.38   400.4 1008.12   408.6  1009.6   435.8 1011.55
#Mann= 3 ,-1,0
       0      .1       0  190.23    .045       0   204.8      .1       0
Bank Sta=190.23,204.8
XS Rating Curve= 0 ,0
Exp/Cntr(USF)=0,0
Exp/Cntr=0.3,0.1

Type RM Length L Ch R = 1 ,7062    ,205.2,210.3,212.5
XS GIS Cut Line= 2
1626867.29753404479387.1158083531626488.53400113479584.317647752
#Sta/Elev= 30
       0 1019.95     4.8 1017.78    23.3 1012.66    34.7 1008.53    67.7 1004.59
    86.2  997.07   115.8   981.7   141.7  974.86   149.1     971   152.8  968.11
   163.3  957.23     175  947.13   189.7  931.84   202.6  924.85   212.3  923.63
     223  923.77  227.39924.8189   234.1  928.35   245.2  938.55     261  950.82
   267.4   957.5   278.5  966.85   311.8  987.37   337.7  1000.7   356.2 1007.63
   363.6 1009.39   385.8 1012.22   397.2 1015.72   411.7 1022.28     427 1033.76
#Mann= 3 ,-1,0
       0      .1       0   202.6    .045       0  227.39      .1       0
Bank Sta=202.6,227.39
XS Rating Curve= 0 ,0
Exp/Cntr(USF)=0,0
Exp/Cntr=0.3,0.1

Type RM Length L Ch R = 1 ,6851    ,131.1,130.4,129.4
XS GIS Cut Line= 3
1626810.78971518479277.4613643171626633.23935087479288.650889922
1626401.43888172479330.416864415
#Sta/Elev= 30
       0 1007.61    10.1 1003.43      20 1002.39    39.7   998.6    82.4  974.49
   102.2  966.55   125.5  959.96   144.9  952.88     158  945.48   181.8  927.02
  198.04  917.97   204.4  916.56   221.1     918   224.4  920.18   231.4  926.86
   241.1  934.04   251.1  943.79   277.8  968.11   281.1  970.68   287.8  974.16
   294.4  979.51   301.1  983.99   311.1  988.33   324.4  991.99   337.8  998.88
   351.1 1001.25   367.8 1006.55   384.4  1009.1   391.1 1010.74   413.4 1021.01
#Mann= 3 ,-1,0
       0      .1       0  198.04    .045       0   221.1      .1       0
Bank Sta=198.04,221.1
XS Rating Curve= 0 ,0
Exp/Cntr(USF)=0,0
Exp/Cntr=0.3,0.1

Type RM Length L Ch R = 1 ,6721    ,98.8,98.2,97.4
XS GIS Cut Line= 2
1626784.11178785479112.0499103461626375.12113351479219.535625085
#Sta/Elev= 30
       0 1010.44    20.9  1004.1    34.3 1003.07    47.3  998.73    57.5  997.19
    64.3  994.85    67.7   993.2    81.2  982.75    88.1  978.59   111.8  967.74
   125.3  960.21   172.8  938.09   176.2  935.53     183  927.61   193.8  917.63
     200  914.98  208.32913.9623   220.3   913.3   227.1  913.97     244  924.52
     261  930.57   270.7  940.51   298.3  965.92   305.1  970.18   329.8  982.46
   342.4  989.63   359.3  996.24   383.5 1001.93   410.3 1006.61   422.9 1011.56
#Mann= 3 ,-1,0
       0      .1       0  208.32    .045       0   227.1      .1       0
Bank Sta=208.32,227.1
XS Rating Curve= 0 ,0
Exp/Cntr(USF)=0,0
Exp/Cntr=0.3,0.1

Type RM Length L Ch R = 1 ,6623    ,179.1,178.4,177.6
XS GIS Cut Line= 2
1626747.43961607479004.9862440421626339.84381422479143.238333588
#Sta/Elev= 30
       0 1013.37     6.1 1012.53    30.4 1004.09    44.6 1001.97    54.6  997.99
    82.3  980.97   106.8  967.44   119.6  961.74   130.8  953.99   137.8  948.12
     148  942.37   166.1  932.61   196.7  918.78   204.9  912.69   210.5  910.98
   217.4  910.48  221.29910.9917   234.8  918.74   259.3  930.36   269.4  937.39
   286.7  951.71   300.4  960.55   310.9   966.3   326.7     973   341.7  982.06
   357.6  988.23   373.3  995.46   404.5 1002.62   421.8 1004.05   430.4 1006.81
#Mann= 3 ,-1,0
       0      .1       0   210.5    .045       0  221.29      .1       0
Bank Sta=210.5,221.29
XS Rating Curve= 0 ,0
Exp/Cntr(USF)=0,0
Exp/Cntr=0.3,0.1

Type RM Length L Ch R = 1 ,6444    ,339.5,341.8,340.8
XS GIS Cut Line= 2
1626680.28512392478824.9696292441626282.44344929478994.802413669
#Sta/Elev= 30
       0 1034.41    24.1 1023.49    40.3 1010.08    47.4 1005.77    65.3 1000.82
    79.5  999.57    93.8  994.32   101.6  990.48   111.6  982.93   122.3   971.7
     133  962.01   164.1  928.59   186.6  909.34  189.33907.8319   196.6  906.85
   204.1  907.83   222.2   908.8   243.6  917.36   254.3  920.45   268.6  919.41
   272.2  921.12   279.3  927.19   286.4  931.81   309.1  942.04   329.2  956.36
   357.8  969.65   372.1  978.57   394.1  988.23   418.4  994.52   432.6  996.78
#Mann= 3 ,-1,0
       0      .1       0  189.33    .045       0   204.1      .1       0
Bank Sta=189.33,204.1
XS Rating Curve= 0 ,0
Exp/Cntr(USF)=0,0
Exp/Cntr=0.3,0.1

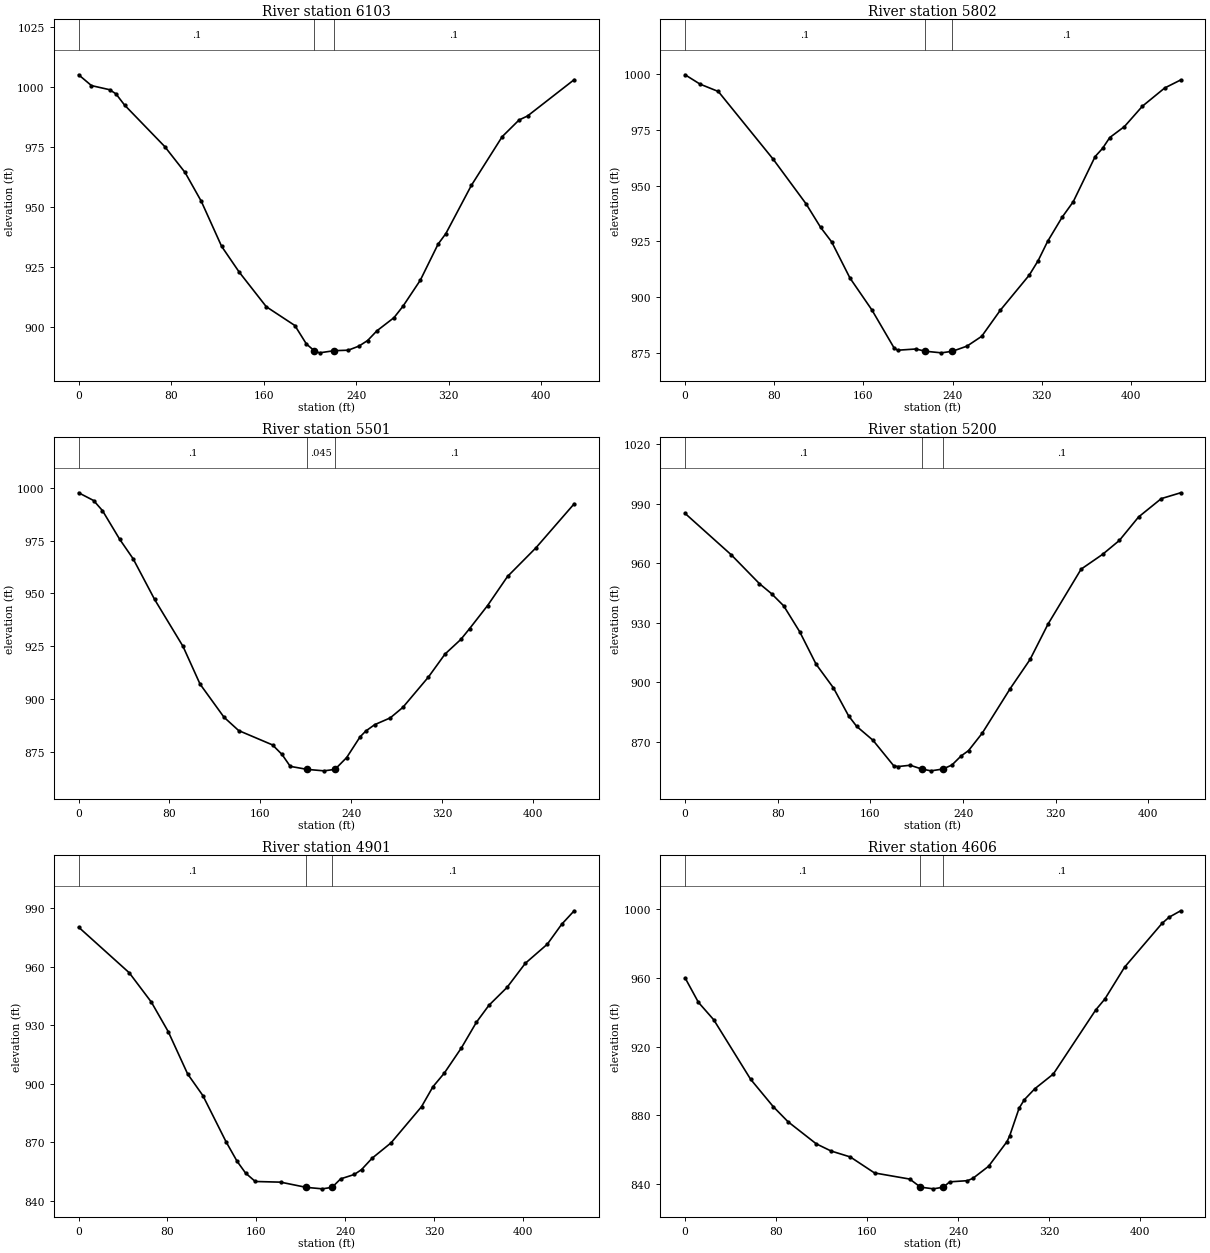
Type RM Length L Ch R = 1 ,6103    ,293.3,300.7,302.6
XS GIS Cut Line= 6
1626486.25411335478594.7396305951626404.62862043478626.261877254
1626334.54313068478652.9645797611626241.87238425478690.606564835
1626175.85644017478728.2656102631626095.17156218478767.652998671
#Sta/Elev= 30
       0    1005    11.1 1000.49    26.7  998.79    32.2  997.08    39.7  992.39
    74.4  975.11      92   964.3     106  952.31   123.6  933.52   138.8  922.79
   162.2  908.38   186.9  900.55   196.9  892.83  203.63890.0654   208.2  889.17
  220.87890.0652     233  890.27   242.3  891.98   249.8  894.31   257.8  898.34
   272.6  903.84   280.2  908.49   295.3  919.41   310.7  934.48   317.4  938.85
   339.4  958.89   366.1  979.23   380.7  986.18     388  987.84   428.3 1002.96
#Mann= 3 ,-1,0
       0      .1       0  203.63    .045       0  220.87      .1       0
Bank Sta=203.63,220.87
XS Rating Curve= 0 ,0
Exp/Cntr(USF)=0,0
Exp/Cntr=0.3,0.1

Type RM Length L Ch R = 1 ,5802    ,281.2,301.3,308.2
XS GIS Cut Line= 6
1626387.54860209478405.4309540841626290.62556759478403.901757672
1626206.36589359478405.6192739161626105.56753875478409.590722665
1626030.65233426478413.1573165951625943.25159043478417.318069428
#Sta/Elev= 30
       0  999.63    13.4  995.45    29.8  992.15      79  961.84   108.5  941.86
   121.6  931.29   131.5  924.79   147.9  908.62   167.6  894.32   187.3  877.48
   190.6  876.28     207  876.83  215.58875.8255     230  875.11   239.9875.8264
   252.9  878.11   266.1  882.51   282.7  894.12   308.8  909.93   316.8  916.43
   325.2  924.97   338.3  935.87   348.2  942.74   367.9  963.02   374.5  966.64
     381  971.52   394.2  976.45   410.3  985.56   430.3  993.72   444.6   997.3
#Mann= 3 ,-1,0
       0      .1       0  215.58    .045       0   239.9      .1       0
Bank Sta=215.58,239.9
XS Rating Curve= 0 ,0
Exp/Cntr(USF)=0,0
Exp/Cntr=0.3,0.1

Type RM Length L Ch R = 1 ,5501    ,309.3,300.2,294.2
XS GIS Cut Line= 6
1626427.85298343478290.9315111791626352.36921051478241.305954263
1626296.08356193478189.5120945871626241.36713593478105.549664095
1626188.64184767478049.0553545061626112.05177775 477998.06234625
#Sta/Elev= 30
       0  997.57    13.2  993.91      21  989.13    36.1  975.64      48  966.37
    66.9  947.17    91.9  924.99   106.9  907.17     128  891.51   140.9  885.21
   170.7  878.43   179.1  873.91   186.3   868.3  201.21866.8646     216  866.18
  225.69 866.865     236  872.46   247.8  882.24   252.9  885.02   260.7  888.01
   274.3  891.18   285.4  896.13     308  910.52   322.6  921.37   336.5  928.27
   344.3  933.43     360  944.24   377.6  958.01   402.6  971.54   436.3  992.36
#Mann= 3 ,-1,0
       0      .1       0  201.21    .045       0  225.69      .1       0
Bank Sta=201.21,225.69
XS Rating Curve= 0 ,0
Exp/Cntr(USF)=0,0
Exp/Cntr=0.3,0.1

Type RM Length L Ch R = 1 ,5200    ,297.5,299.8,302.7
XS GIS Cut Line= 6
1626552.93869126477948.1441390071626467.97495042477918.545444921
1626397.50265042477891.8899864261626306.07173093 477851.33462134
1626238.16208984477819.5020078421626158.93554226477782.361990258
#Sta/Elev= 30
       0   985.2    39.9  964.31    64.2  949.79    74.6  944.76    85.1  938.64
      99  925.51   113.1   909.2   128.1  897.25   141.1  883.24   148.1   877.9
   162.2  870.89     180   858.1   183.7  857.63   194.4   858.3  204.31856.3779
   212.3  855.48  222.42856.3772   230.3  858.39   238.3  862.99   244.7  865.68
   256.5  874.45   280.7  896.96   297.8  911.59   313.3  929.42   341.9  957.13
   360.4  964.56   374.9  971.58   391.5  983.42   411.1  992.66   427.8   995.6
#Mann= 3 ,-1,0
       0      .1       0  204.31    .045       0  222.42      .1       0
Bank Sta=204.31,222.42
XS Rating Curve= 0 ,0
Exp/Cntr(USF)=0,0
Exp/Cntr=0.3,0.1

Type RM Length L Ch R = 1 ,4901    ,305.6,294.2,275.3
XS GIS Cut Line= 6
1626634.68655926477742.6087889221626568.67094326477683.975047916
1626511.93844518477634.5988343361626430.72863384477576.219686002
1626351.34263776477552.6439457541626251.55313918477545.964825258
#Sta/Elev= 30
       0  980.42    45.6  957.02    65.5  941.98    80.7  926.84    98.2   905.1
   111.9  894.03   132.7  870.42   142.7  860.34   150.4  854.26   159.1  849.97
   181.9  849.63  204.91846.9635   219.5   846.2  228.21 846.963     236  851.32
   248.3  853.57   254.8  856.07   264.3   861.9   281.4   869.8   308.8  888.32
   319.1  898.57   329.3  905.53   344.8  918.56   358.3  931.69   369.5  940.33
   385.9  949.56   402.3  961.89   422.1  971.69     435  981.87   446.3  988.83
#Mann= 3 ,-1,0
       0      .1       0  204.91    .045       0  228.21      .1       0
Bank Sta=204.91,228.21
XS Rating Curve= 0 ,0
Exp/Cntr(USF)=0,0
Exp/Cntr=0.3,0.1

Type RM Length L Ch R = 1 ,4606    ,298.5,304.3,306.1
XS GIS Cut Line= 6
1626601.44581209477278.0057155041626516.91022001477315.017124429
1626450.93987951477353.9094350931626375.25171067477419.419474676
1626321.88731609477472.4046049271626236.82547835477505.845154837
#Sta/Elev= 30
       0  960.06    11.7  945.82    25.2  935.62    57.6  900.95    77.5  884.99
    90.5  876.18   115.3  863.31   128.4  859.11   145.2  855.67   166.5  846.34
   197.5  842.76  206.91838.0614   218.3  837.07  227.07838.0604   232.6  841.15
   248.2  841.83     253  843.19   266.8  850.24     283  864.64   285.4  868.13
   293.6  884.09   298.2  889.04   307.4  895.42   323.7  904.03     361  941.42
     369  947.75   386.3   966.3   419.2  991.82   425.4  995.42   435.6   999.2
#Mann= 3 ,-1,0
       0      .1       0  206.91    .045       0  227.07      .1       0
Bank Sta=206.91,227.07
XS Rating Curve= 0 ,0
Exp/Cntr(USF)=0,0
Exp/Cntr=0.3,0.1

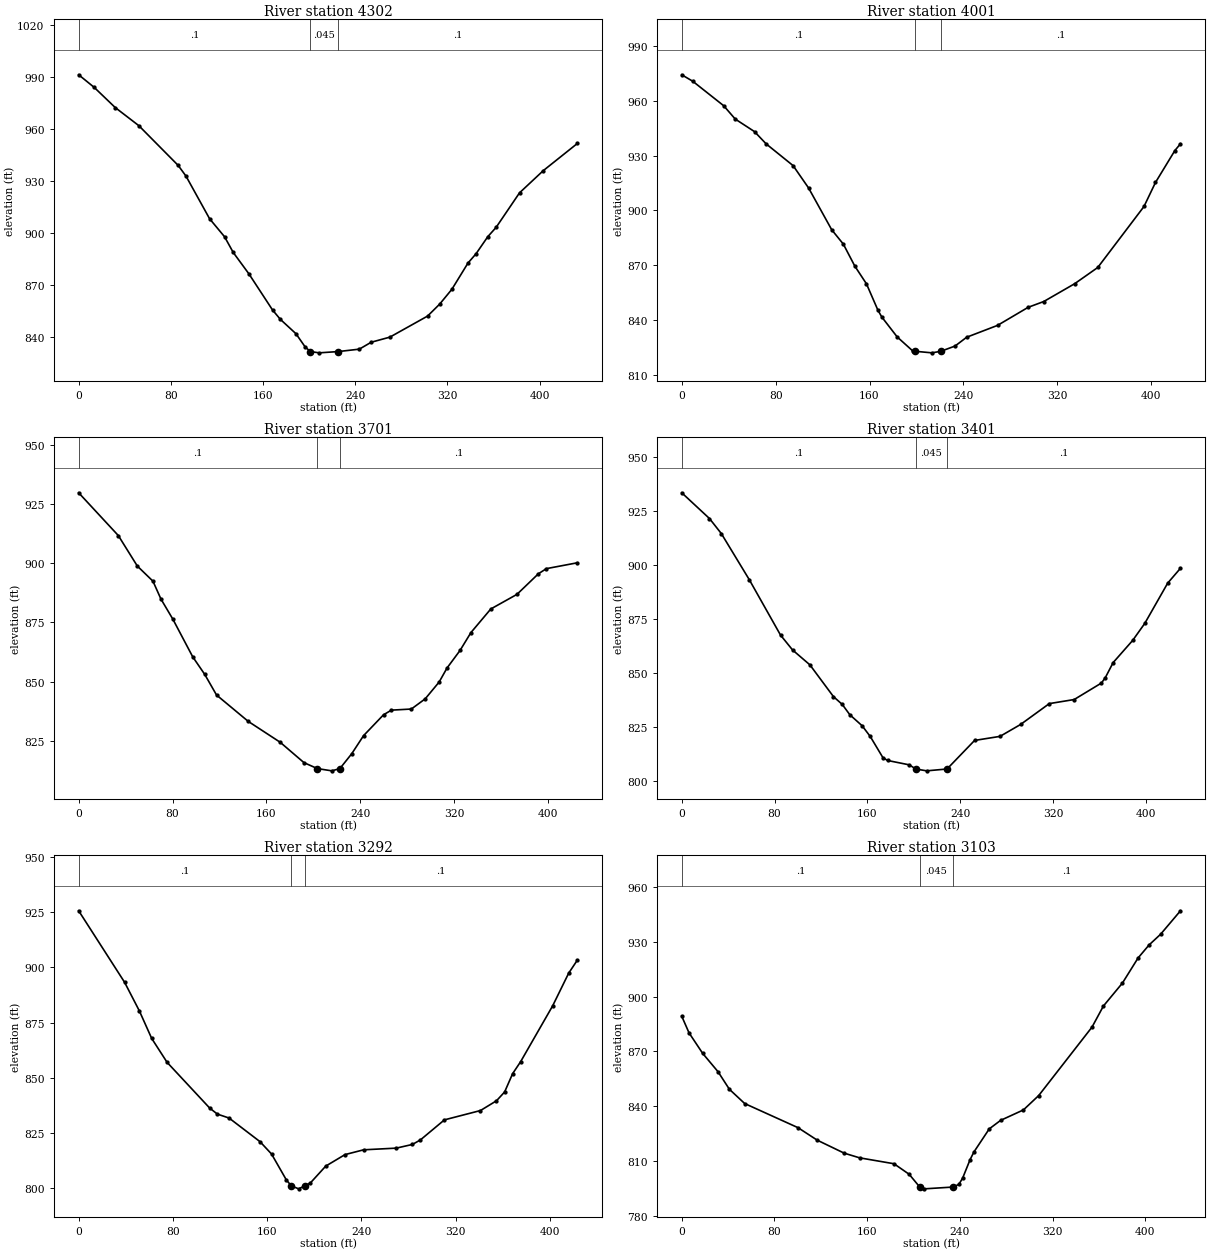
Type RM Length L Ch R = 1 ,4302    ,296.6,300.5,301.9
XS GIS Cut Line= 6
1626588.40318726477032.1364565941626504.26982534477056.173810095
1626432.15514018477076.777443424 1626336.2514606477105.277058333
1626263.81689417477132.8665700851626175.34889525477160.440333843
#Sta/Elev= 30
       0  991.17    13.5   983.9    31.7  972.32    52.2  961.88    86.3  939.03
    93.1  932.87   113.6   908.3   126.6  897.92   134.1   888.9   147.7  876.59
   168.2  855.79     175  850.39   188.5  842.15   196.4  834.62  200.99831.8556
   208.7  831.12  225.27831.8567   243.5  833.24   253.8  837.22     270  840.16
   302.7  852.27   313.2  859.15   323.8  867.69   337.8  882.82   344.7  888.09
     355  898.01   362.2  903.35   382.5  923.22   403.1  935.99   432.7  951.65
#Mann= 3 ,-1,0
       0      .1       0  200.99    .045       0  225.27      .1       0
Bank Sta=200.99,225.27
XS Rating Curve= 0 ,0
Exp/Cntr(USF)=0,0
Exp/Cntr=0.3,0.1

Type RM Length L Ch R = 1 ,4001    ,303.1,300,298.4
XS GIS Cut Line= 6
1626508.25505359 476800.754701511626420.96257725476807.066696763
1626346.08346193476811.3491685091626246.21128634476816.405588835
1626171.30723667476820.1982321741626083.91928808476824.622764006
#Sta/Elev= 30
       0  974.28     9.4  970.72    35.7  957.35    45.6  950.02      62  943.16
    71.9  936.46    94.9  924.53   108.1  912.27   127.8  889.41   137.7  881.56
   147.5  869.49   157.4  859.82   167.2  845.33   170.5  841.62   183.6  830.73
   196.8  823.09  198.98 822.878   213.2  822.03  220.74822.8759   232.9  825.75
   242.8  830.58   269.1  837.06   295.2  846.96   308.5  850.13   334.8  859.87
   354.5  868.76   393.9  902.16   403.7  915.32   420.2  932.77     425  936.51
#Mann= 3 ,-1,0
       0      .1       0  198.98    .045       0  220.74      .1       0
Bank Sta=198.98,220.74
XS Rating Curve= 0 ,0
Exp/Cntr(USF)=0,0
Exp/Cntr=0.3,0.1

Type RM Length L Ch R = 1 ,3701    ,290.4,300.1,309.6
XS GIS Cut Line= 6
1626402.70047468476483.977119833 1626317.9755785476505.840265095
1626245.31889968476524.4412777571626148.44310917476549.241753086
1626075.78610225 476567.842437671625991.01986758476589.543181673
#Sta/Elev= 30
       0  929.75    33.8  911.68      50   898.8    63.3  892.42    70.1  884.89
    80.3  876.35    97.2  860.47   107.4  853.08   117.5  844.34   144.6  833.18
   171.7  824.41     192  815.79  203.43 813.281   215.7  812.33  222.59813.2786
   232.7  819.55   242.8   827.2   259.8     836   266.5  837.96   283.5  838.43
   295.3  842.73   307.2  849.84   313.9  855.75     325  863.17   334.3  870.73
   351.2  880.68   373.5  886.85   391.8  895.56   398.6  897.72     425  900.19
#Mann= 3 ,-1,0
       0      .1       0  203.43    .045       0  222.59      .1       0
Bank Sta=203.43,222.59
XS Rating Curve= 0 ,0
Exp/Cntr(USF)=0,0
Exp/Cntr=0.3,0.1

Type RM Length L Ch R = 1 ,3401    ,116.3,109.6,107.6
XS GIS Cut Line= 6
1626374.26844493476318.6605213431626288.35851176476295.130712762
1626217.77138259476267.7052426791626130.22759442476219.145300418
1626060.07255101476190.7972600011625973.04844683476171.447561175
#Sta/Elev= 30
       0  933.48    23.9  921.53    34.1  914.56    58.1  893.26    85.1  867.49
    95.5  860.57   110.4  853.69   130.7  838.96   138.3  835.33   144.8  830.56
   155.4  825.45   162.4  820.47   173.3  810.67   177.3  809.35     196  807.32
  201.67805.3936     211  804.54  228.57805.3934   252.3  818.64   274.2  820.52
   291.9  826.03   316.7  835.72   338.1   837.6   361.6  845.26     365  847.81
   371.7  854.75   388.5  865.01   398.9  872.88   418.7   891.6   429.7  898.48
#Mann= 3 ,-1,0
       0      .1       0  201.67    .045       0  228.57      .1       0
Bank Sta=201.67,228.57
XS Rating Curve= 0 ,0
Exp/Cntr(USF)=0,0
Exp/Cntr=0.3,0.1

Type RM Length L Ch R = 1 ,3292    ,184.6,188.7,193.5
XS GIS Cut Line= 3
1626399.98886411476130.4354761371626153.35056359476143.287596015
1625983.21297664476096.163156462
#Sta/Elev= 30
       0  925.65      39  893.27    51.5  880.37      62  867.87    75.1  857.02
   111.2  836.36   117.8  833.59   127.7  831.82     154  821.12   163.8  815.52
   176.4  803.76  180.57801.1221   186.8  799.76     192  801.12   196.7  802.39
   209.8  810.05   226.2  815.27     242  817.43   269.7  818.19   283.4  819.86
   290.2  821.91   310.6  830.99   341.2  835.21   354.8  839.63   361.7  843.61
   368.5   851.9   375.3  857.33   402.5  882.61   416.1   897.4   423.5  903.34
#Mann= 3 ,-1,0
       0      .1       0  180.57    .045       0     192      .1       0
Bank Sta=180.57,192
XS Rating Curve= 0 ,0
Exp/Cntr(USF)=0,0
Exp/Cntr=0.3,0.1

Type RM Length L Ch R = 1 ,3103    ,211.8,217.2,213.8
XS GIS Cut Line= 6
1626385.72249025475983.2645385861626293.60029918475978.457789674
1626218.91081601475967.4916042541626119.06226243475961.138598591
1626044.15165108475957.4932646751625956.76271826475953.240976587
#Sta/Elev= 30
       0  889.29     6.3  880.16    18.1  868.91    31.3   858.9    41.1  849.28
    54.3  841.47   100.3  828.25   116.9   821.4   140.1   814.3   153.4  811.73
   183.1  808.49   196.2  802.72  205.38795.7075   209.4  794.74   233.8  795.71
     239  797.12   242.3  800.54   248.8  810.78   252.1  814.95   265.3  827.58
   275.1  832.25   294.8  837.98     308  845.86     354  883.37   363.8  894.89
   380.2  907.46   393.7  921.21   403.2  928.35   413.1  934.18   430.3  947.07
#Mann= 3 ,-1,0
       0      .1       0  205.38    .045       0   233.8      .1       0
Bank Sta=205.38,233.8
XS Rating Curve= 0 ,0
Exp/Cntr(USF)=0,0
Exp/Cntr=0.3,0.1

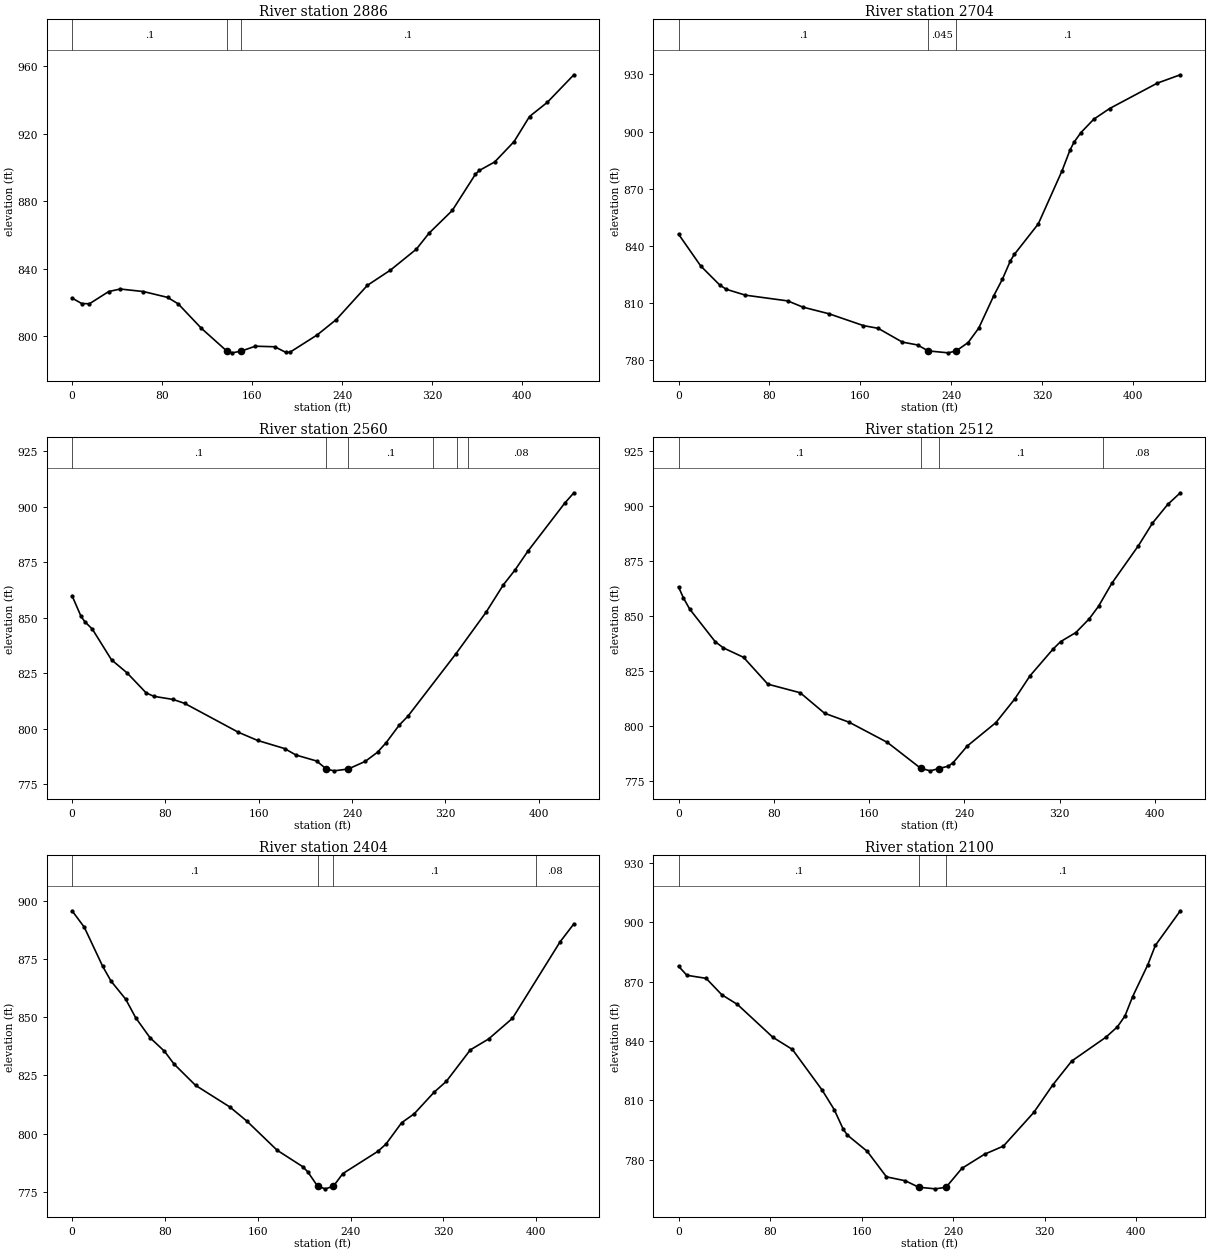
Type RM Length L Ch R = 1 ,2886    ,177.5,181.7,176.4
XS GIS Cut Line= 2
1626372.54820695475752.7617632171625946.07821556 475882.16895044
#Sta/Elev= 30
       0  822.47     8.5  819.23    15.4  819.07    32.6  826.35    42.8  827.83
    63.4  826.33    84.8  822.87    94.3  819.01   114.8  804.55  137.46790.9963
   142.3  789.95  150.33790.9998   162.8  793.89     180  793.55     190  790.18
   193.7  790.38   217.7  800.57   234.7  809.71   262.3  830.02   282.8  839.06
   305.8   851.5   317.1     861   337.7  874.45   358.3  896.01   361.7  898.19
   375.4  903.26   392.6  915.35   406.3  930.22   422.1  938.64   445.7  955.01
#Mann= 3 ,-1,0
       0      .1       0  137.46    .045       0  150.33      .1       0
Bank Sta=137.46,150.33
XS Rating Curve= 0 ,0
Exp/Cntr(USF)=0,0
Exp/Cntr=0.3,0.1

Type RM Length L Ch R = 1 ,2704    ,122,144.5,153.2
XS GIS Cut Line= 4
1626308.07496451475647.121519122  1626143.989201475675.807841414
1626080.87929196475747.5236471421625912.20371689475808.912376845
#Sta/Elev= 30
       0  846.13    19.5  829.44    36.1  819.52    41.9   817.2    58.9  814.08
    96.1  811.07   109.4  807.81   132.4  804.31   162.7   798.1   175.7  796.66
   196.9  789.44   210.4  787.92  219.65784.8126   237.4  783.79  244.43784.8203
   254.9  789.22   264.2  796.77   277.3  813.65     285  822.45   292.1  832.19
   295.6  835.55   316.6  851.52   337.5   879.4   344.5   890.3     348  894.38
   354.1  899.47   365.4   906.5   379.4  912.13   421.3  925.45   441.6  929.85
#Mann= 3 ,-1,0
       0      .1       0  219.65    .045       0  244.43      .1       0
Bank Sta=219.65,244.43
XS Rating Curve= 0 ,0
Exp/Cntr(USF)=0,0
Exp/Cntr=0.3,0.1

Type RM Length L Ch R = 1 ,2560    ,45.5,47.2,46.6
XS GIS Cut Line= 3
1626319.38294005475639.9405299821626120.58672657475622.900854541
1625917.65968269475513.433848679
#Sta/Elev= 30
       0  859.98     7.6  850.78    10.8  848.35    17.4  844.91    33.8  831.09
    47.1  825.24    63.5  816.19    70.1  814.65    86.6  813.24    96.5  811.47
   142.6  798.44     159  794.77   182.1  791.12   191.9   788.2   209.6   785.5
  217.93781.8876   224.5  781.07   236.7  781.89   251.3  785.33   261.8  789.45
   269.2  793.76   280.4  801.66   287.9  805.71   328.9  833.74     355  852.66
   369.7  864.92   379.6  871.53   390.7  880.06   422.1  901.58   430.1  906.37
#Mann= 6 ,-1,0
       0      .1       0  217.93    .045       0   236.7      .1       0
  309.53     .08       0  329.53      .1       0  339.53     .08       0
Bank Sta=217.93,236.7
XS Rating Curve= 0 ,0
Exp/Cntr(USF)=0,0
Exp/Cntr=0.3,0.1

Type RM Length L Ch R = 1 ,2512    ,108.6,108.1,108
XS GIS Cut Line= 3
1626321.96470905 475635.293345771626151.56795465 475589.33785746
1625940.89560374475464.380237562
#Sta/Elev= 30
       0  863.18     4.1  858.16     9.4  853.06    30.8  838.25    37.7  835.42
    54.6  831.14      75  818.93   102.2  815.02   122.6  805.71   143.3  801.61
   175.4  792.43   203.4780.6474   211.4   779.5   218.6  780.55   226.6  781.62
   230.6  783.23   242.5  790.81   266.5  801.43   282.2  812.09   295.2  822.76
   314.4  834.82   320.8  838.26   333.7  842.43   344.9  848.65   352.7  854.37
   363.9  864.84   386.2  881.93     398  892.18   410.8  900.69   421.4     906
#Mann= 4 ,-1,0
       0      .1       0   203.4    .045       0   218.6      .1       0
  356.49     .08       0
Bank Sta=203.4,218.6
XS Rating Curve= 0 ,0
Exp/Cntr(USF)=0,0
Exp/Cntr=0.3,0.1

Type RM Length L Ch R = 1 ,2404    ,302.9,304.5,295.7
XS GIS Cut Line= 6
 1626358.7415731475571.3375409251626278.96679826475534.111237422
1626211.62769409475499.570952177   1626124.11573475449.971313834
1626052.52565008475425.2489223331625960.78337951475414.596712679
#Sta/Elev= 30
       0   895.8    10.5  888.76    26.4   871.9    33.6  865.54    46.2   857.8
    54.9  849.75    67.2  841.21    79.6  835.41    87.9  829.89   106.4  820.75
   135.9  811.46   150.6  805.39   176.7  792.85   198.7   785.8   203.1  783.56
  211.65777.3398   218.2  776.25  225.14777.3403   233.3   782.8   263.5  792.36
   270.5  795.49     284  804.68   294.8   808.5   312.1  817.86   322.5  822.46
   343.2     836   358.9  840.67   379.5  849.57   420.5  882.42   432.4  890.17
#Mann= 4 ,-1,0
       0      .1       0  211.65    .045       0  225.14      .1       0
  400.04     .08       0
Bank Sta=211.65,225.14
XS Rating Curve= 0 ,0
Exp/Cntr(USF)=0,0
Exp/Cntr=0.3,0.1

Type RM Length L Ch R = 1 ,2100    ,295.4,297.8,296.5
XS GIS Cut Line= 6
1626338.17074808475155.5909970851626248.00787067475183.075194091
1626170.77278893475206.8920755831626070.66406526475217.067252085
1625996.27641876475227.7516139151625909.80447884475241.862149999
#Sta/Elev= 30
       0  877.77     7.3  873.18    24.1  871.63    37.8  863.34    51.5  858.43
    82.4  841.86    99.5   835.7   125.6  815.07   136.1  805.23   143.9  795.39
   147.6  792.38   164.9  784.19   181.7   771.3   198.2  769.31  209.94766.0463
   224.5  765.24  233.81766.0464   247.6  775.58   267.4  782.73   283.9  786.84
   310.5  803.89     327  817.74   343.6  829.83   373.5  841.89   383.5  847.12
   390.1  852.58   396.8  862.36   410.1  878.52   416.7   888.3   438.5  905.78
#Mann= 3 ,-1,0
       0      .1       0  209.94    .045       0  233.81      .1       0
Bank Sta=209.94,233.81
XS Rating Curve= 0 ,0
Exp/Cntr(USF)=0,0
Exp/Cntr=0.3,0.1