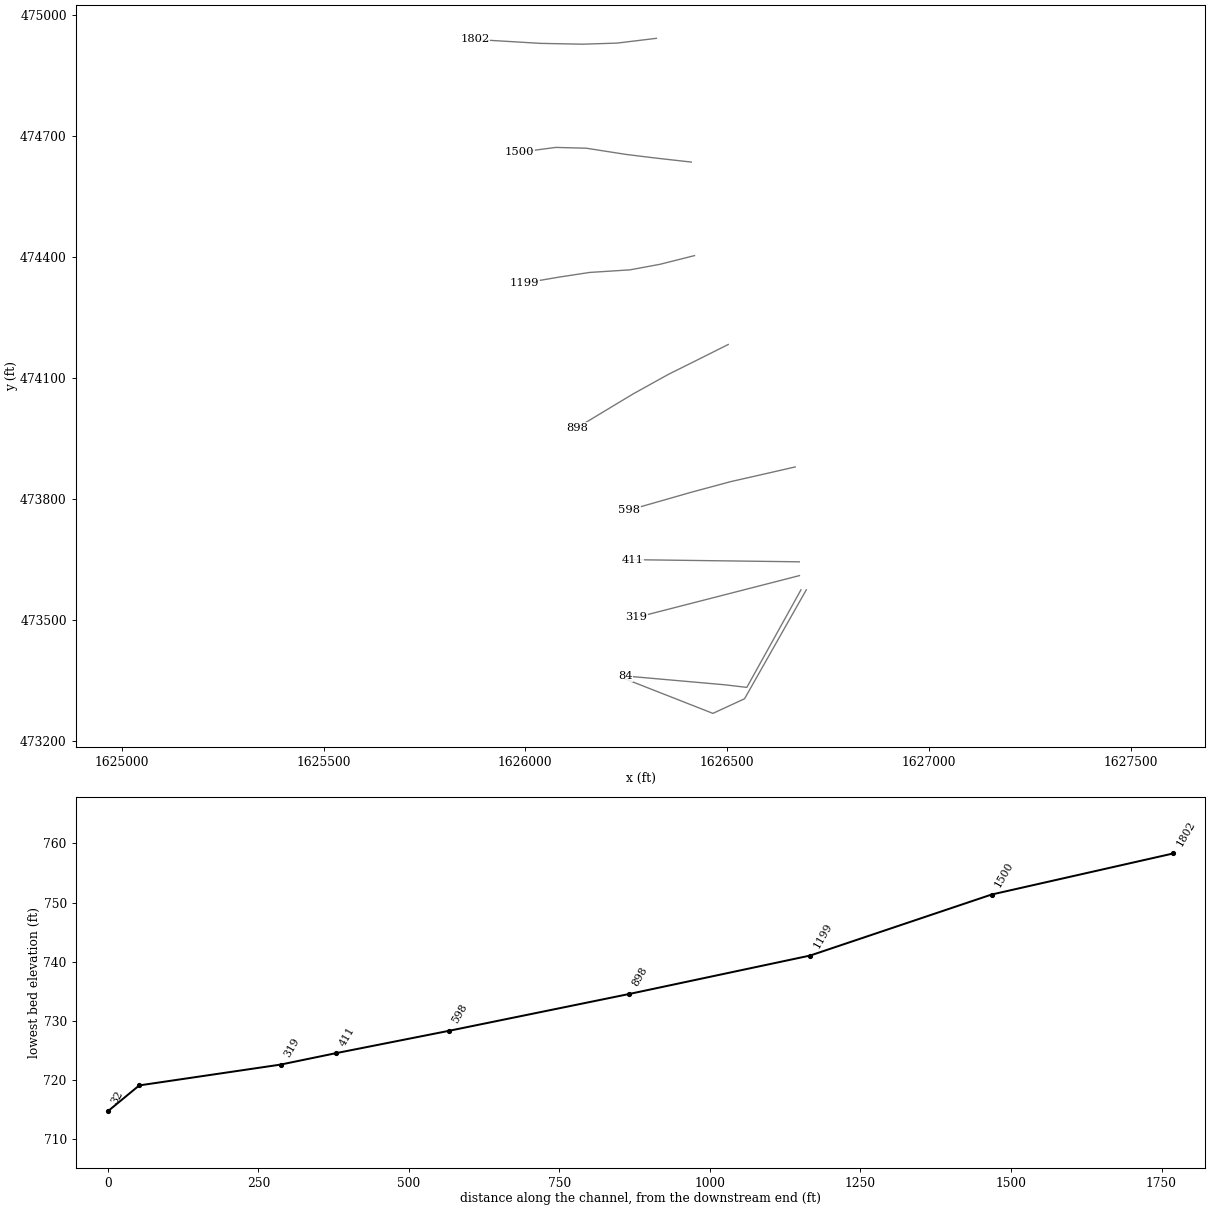
HEC-RAS study WstFkLwrBwmRn.prj: WstFkLwrBwmRn

--- WstFkLwrBwmRn.g01 (geometry) --- (continued)

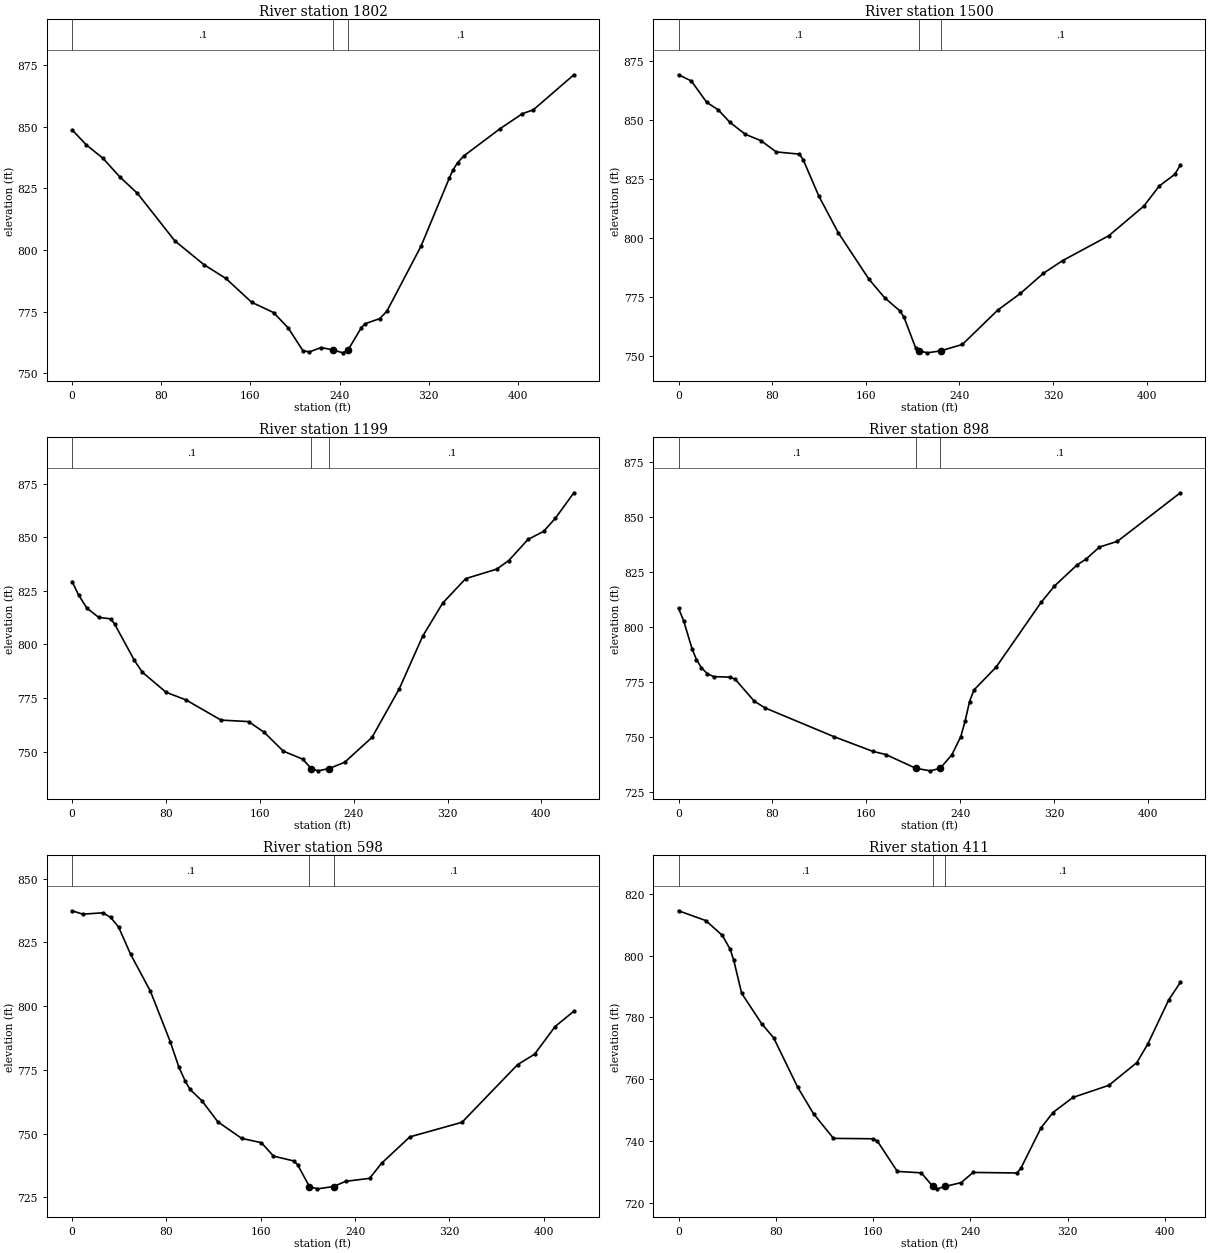
Type RM Length L Ch R = 1 ,1802    ,304.1,302.1,297.7
XS GIS Cut Line= 6
1626324.58645767474941.6389971671626226.95541935474929.827669084
1626141.42835942474927.1291836651626037.58506317474929.164284587
1625962.71972734 474933.656401591625875.37672618474938.896876678
#Sta/Elev= 30
       0  848.79    12.8  842.66    27.8  837.21    42.6  829.78    58.7  822.99
    92.1  803.79   118.4  794.06     138   788.5   161.1  778.85   180.8  774.65
   193.9  768.45   207.1  759.23   212.9  758.67   223.5  760.47  234.25759.4752
   243.1  758.31  247.67759.4742   259.4  768.39   262.8  770.09     276  772.18
   282.5  775.18   313.2  801.65   338.4  829.04   341.7   832.4   345.9   835.4
   351.5  838.17   384.3   849.3   404.1  855.31     414  856.91   450.3   871.1
#Mann= 3 ,-1,0
       0      .1       0  234.25    .045       0  247.67      .1       0
Bank Sta=234.25,247.67
XS Rating Curve= 0 ,0
Exp/Cntr(USF)=0,0
Exp/Cntr=0.3,0.1

Type RM Length L Ch R = 1 ,1500    ,299.3,301.3,303.4
XS GIS Cut Line= 6
1626411.23425026474635.0831798321626324.20325634474644.842346668
1626249.71488826474653.9984963391626150.86502033474669.425630838
1626075.56989534474671.3964274231625985.61010151474659.579193845
#Sta/Elev= 30
       0  868.98    10.9  866.38    24.1  857.31      34   854.1    43.9  848.87
    57.1  843.78    70.3  841.14    83.5  836.34   103.3  835.41   106.6  832.91
   119.8  817.73   136.4  802.22   162.6  782.55     176   774.7   189.4  768.96
   192.7   766.3   202.7  753.28  205.18752.2249   212.6  751.35  224.24 752.223
   242.5   754.9   272.7  769.41     292  776.46   311.7  784.99   328.1  790.35
   367.7  800.93   397.5  813.41   410.7  821.93     424  826.88   428.7  830.77
#Mann= 3 ,-1,0
       0      .1       0  205.18    .045       0  224.24      .1       0
Bank Sta=205.18,224.24
XS Rating Curve= 0 ,0
Exp/Cntr(USF)=0,0
Exp/Cntr=0.3,0.1

Type RM Length L Ch R = 1 ,1199    ,294.7,300.4,302.5
XS GIS Cut Line= 6
1626419.12629484474403.3733414261626333.60481234474381.826796591
1626259.22930492474368.0384383351626159.09433459474361.650327757
1626084.42355217 474350.196610511625997.67963117474335.486338094
#Sta/Elev= 30
       0  829.39     5.7  822.97    12.6  817.01    22.7  812.65    32.8  811.98
    36.2  809.62    53.1   792.6    59.9  787.06    80.2  777.68      97  774.16
     127  764.71   150.4  764.02   163.7  759.04   180.1   750.2   196.6  746.49
  203.85742.0873   209.7  741.03  218.97742.0869   232.3     745   255.7  756.67
   278.9  779.34   298.8  803.83   315.9  819.34   335.5  830.74   361.9  835.17
   372.2  839.16   388.6  849.04   401.9  852.78   411.9  858.91   427.7  870.81
#Mann= 3 ,-1,0
       0      .1       0  203.85    .045       0  218.97      .1       0
Bank Sta=203.85,218.97
XS Rating Curve= 0 ,0
Exp/Cntr(USF)=0,0
Exp/Cntr=0.3,0.1

Type RM Length L Ch R = 1 ,898     ,301.9,299.8,297.2
XS GIS Cut Line= 6
  1626502.677965474183.1634799991626422.67779693474143.096302927
1626354.80982243474109.3312785921626267.28801584 474060.82415776
1626203.04076901474022.1296813341626128.08553834473976.985742763
#Sta/Elev= 30
       0  808.33     4.3  802.77    11.6  789.87    15.3  785.04    19.5  781.37
    24.4  778.73    29.9  777.33      44  777.09    48.3  776.12    64.7  766.09
      74  763.06   132.6  750.03   165.6  743.39   176.9  741.91  202.25 735.684
   214.6  734.53  223.11735.6831   233.1   741.9   240.6  750.04   244.4   757.3
   248.1  766.02   251.9  771.28   270.8  781.67   309.1  811.04   320.5  818.47
   339.7  828.03   347.4  830.69   358.8  836.15   374.2  838.79   427.8  860.83
#Mann= 3 ,-1,0
       0      .1       0  202.25    .045       0  223.11      .1       0
Bank Sta=202.25,223.11
XS Rating Curve= 0 ,0
Exp/Cntr(USF)=0,0
Exp/Cntr=0.3,0.1

Type RM Length L Ch R = 1 ,598     ,189.9,187.6,184.3
XS GIS Cut Line= 6
1626668.57855184473879.7762915051626583.07248926473860.238272846
1626509.73733409473843.6087129271626413.11383967473817.633699253
1626341.00702851 473797.007100091626256.88843034473772.945140332
#Sta/Elev= 30
       0  837.42     9.2  836.09      26  836.62    32.7  834.84    39.5  830.99
    49.6  820.37    66.4  805.89    83.2  786.11    90.6  776.02    96.1  770.44
     100  767.32   110.1  762.86   123.6   754.6   143.8  748.11   160.6  746.38
   170.8  741.14   187.8  739.25   191.2  737.79  201.29729.1862   208.1  728.29
  221.72729.1844   231.9  731.23   252.3  732.41   262.5  738.35   286.4  748.68
   330.7  754.42   377.8  777.05   392.2  781.12   409.6  791.99   425.5     798
#Mann= 3 ,-1,0
       0      .1       0  201.29    .045       0  221.72      .1       0
Bank Sta=201.29,221.72
XS Rating Curve= 0 ,0
Exp/Cntr(USF)=0,0
Exp/Cntr=0.3,0.1

Type RM Length L Ch R = 1 ,411     ,89,91.8,93.4
XS GIS Cut Line= 2
1626678.75662584473644.7279731911626266.21944457473650.016911413
#Sta/Elev= 30
       0  814.48    22.4  811.31      36  806.52    42.5     802    45.4  798.46
    51.9  787.79    68.3  777.97    78.2  773.38    97.9  757.43     111  748.81
   127.4  740.84   160.2  740.71   163.5  739.95   179.9  730.15   199.6  729.69
   209.1 725.274   212.7  724.51   219.3  725.29   232.4  726.53   242.2  729.82
   278.3  729.64   281.6  731.26     298   744.2   307.9  749.21   324.3  754.09
   353.8     758   376.8  765.33   385.9   771.4     403  785.61   412.6  791.29
#Mann= 3 ,-1,0
       0      .1       0   209.1    .045       0   219.3      .1       0
Bank Sta=209.1,219.3
XS Rating Curve= 0 ,0
Exp/Cntr(USF)=0,0
Exp/Cntr=0.3,0.1

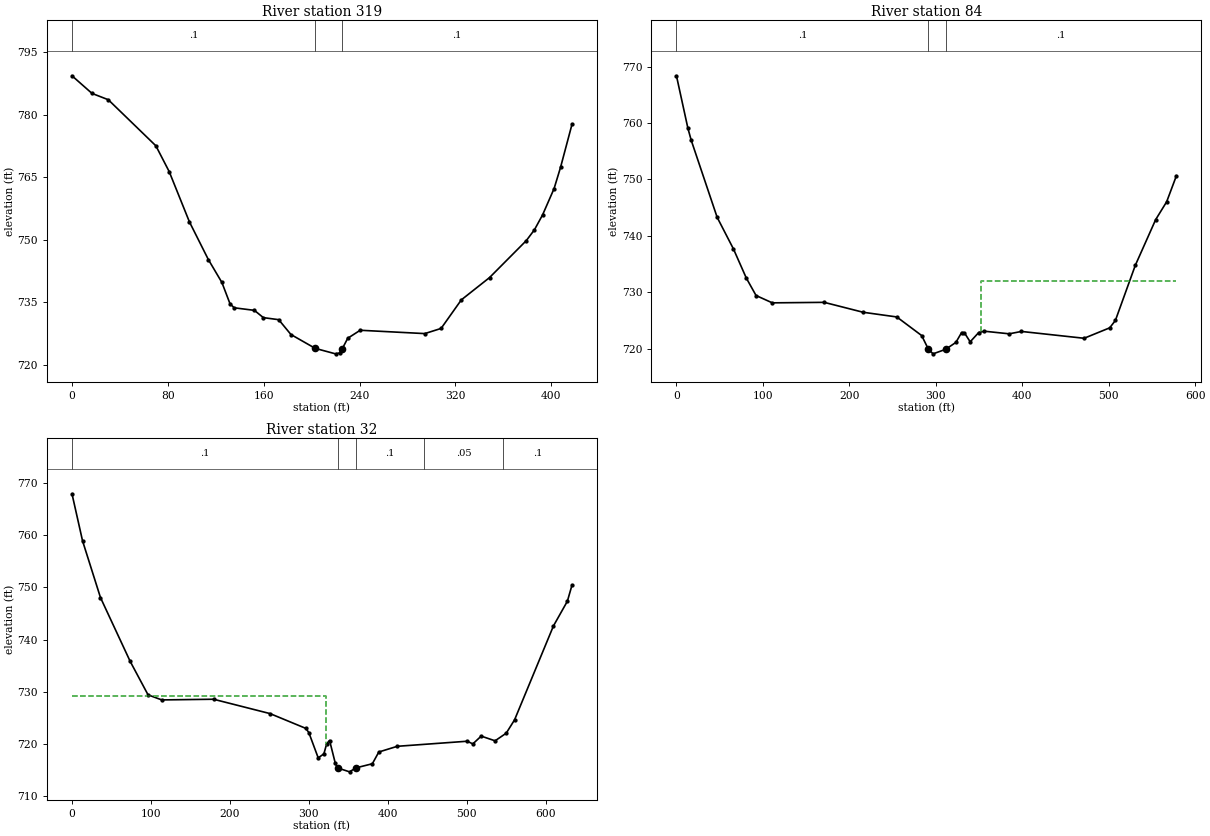
Type RM Length L Ch R = 1 ,319     ,236.9,234.7,229.8
XS GIS Cut Line= 2
1626679.09526309473610.5541795951626274.97958568473506.874783141
#Sta/Elev= 30
       0  789.33    16.7   785.1    30.3  783.58      70  772.52    81.1  766.34
      98  754.26   113.8  745.21   125.1  739.71   131.9  734.58   135.4  733.63
   152.2  733.02   159.7  731.27   172.5  730.78   182.7  727.22     203  723.89
   219.9  722.58   223.3  722.79  225.63 723.845   230.1  726.32   240.5  728.24
   294.4  727.44     308  728.68   324.9  735.54   348.4  740.88   379.1  749.76
   385.9  752.36   392.7  755.94   402.3  762.26   407.7  767.37   417.2  777.64
#Mann= 3 ,-1,0
       0      .1       0     203    .045       0  225.63      .1       0
Bank Sta=203,225.63
XS Rating Curve= 0 ,0
Exp/Cntr(USF)=0,0
Exp/Cntr=0.3,0.1

Type RM Length L Ch R = 1 ,84      ,43.9,52.1,56.1
XS GIS Cut Line= 4
 1626682.8528626473575.3093745981626548.71905166473333.618269607
1626494.67954424473340.0080317181626248.08554373473361.840503141
#Sta/Elev= 30
       0  768.36    13.3  759.02    17.1  756.92    47.1  743.26    65.9  737.67
    80.9  732.47    92.1   729.4   110.9   728.1   170.9  728.19     216  726.43
   254.9   725.6   283.7   722.3  291.44719.8826   296.9  719.06  311.44719.8632
   323.3  721.09   329.9  722.84   333.2  722.77   339.8  721.19   349.7  722.84
   356.3  723.07     385  722.61   399.1  723.03   471.6  721.82   501.2  723.67
   507.8  724.98   530.8  734.74   554.4  742.86   567.1  746.02   578.4  750.64
#Mann= 3 ,-1,0
       0      .1       0  291.44    .045       0  311.44      .1       0
#XS Ineff= 2 , 0
                           352.4          732.01
Permanent Ineff=
       F       F
Bank Sta=291.44,311.44
XS Rating Curve= 0 ,0
Exp/Cntr(USF)=0,0
Exp/Cntr=0.3,0.1

Type RM Length L Ch R = 1 ,32      ,,,
XS GIS Cut Line= 4
1626696.07644223473575.3192245921626543.05828897473305.402105882
1626464.71953036473269.2368379291626244.17832812473355.744905822
#Sta/Elev= 30
       0  767.93    13.4  758.91    36.1  748.06    73.8  735.82    96.4  729.43
   113.8  728.46   179.4  728.59     251  725.84   296.3  723.01   300.1  722.21
     312  717.36   319.2  718.14   322.8  720.11   326.4  720.69   333.7   716.3
  336.48715.4413   351.7  714.69   359.6 715.442   380.6  716.24   388.8  718.49
   412.2  719.58   500.8  720.55   507.9  720.04   518.5  721.53   536.1  720.63
   550.2  722.09   560.8  724.65   610.1  742.64   627.7  747.36   633.5  750.41
#Mann= 5 ,-1,0
       0      .1       0  336.48    .045       0   359.6      .1       0
  446.56     .05       0  546.56      .1       0
#XS Ineff= 2 , 0
           322.1  729.26
Permanent Ineff=
       F       F
Bank Sta=336.48,359.6
XS Rating Curve= 0 ,0
Exp/Cntr(USF)=0,0
Exp/Cntr=0.3,0.1
LCMann Table=0

Chan Stop Cuts=-1
Use User Specified Reach Order=0
Composite Channel Slope=5